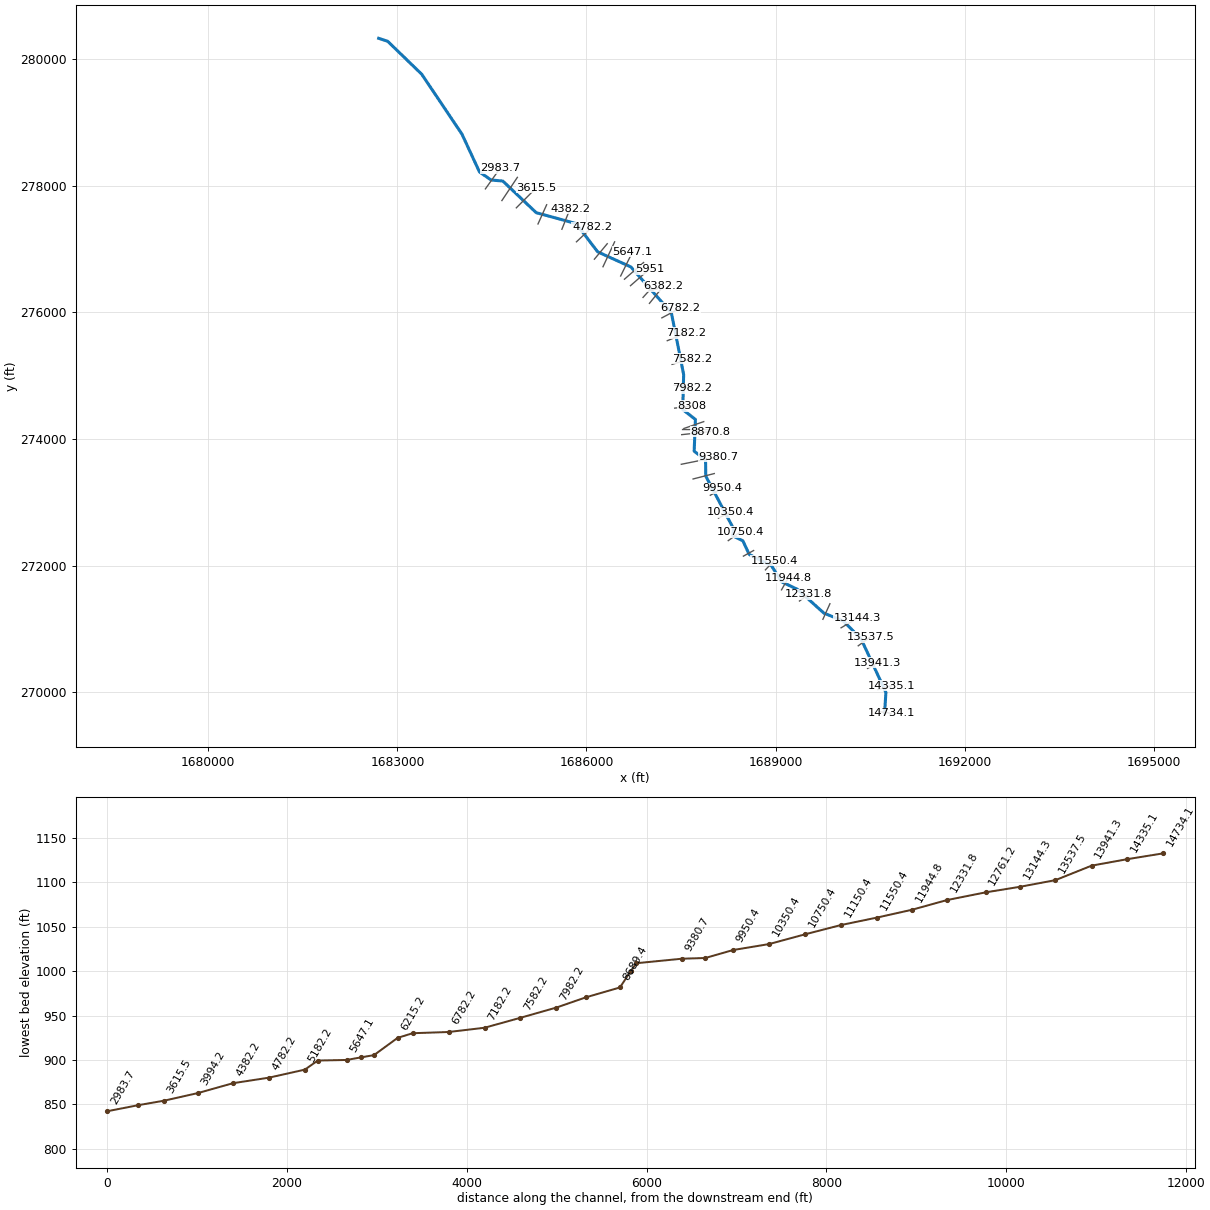
--- MIDDLEILCK.prj (project) ---

Proj Title=MIDDLEILCK
Current Plan=p01
Default Exp/Contr=0,0
English Units
Geom File=g01
Flow File=f01
Plan File=p01
BEGIN DESCRIPTION:
END DESCRIPTION:
DSS Export Rating Curves= 0
DSS Export Rating Curve Sorted= 0
DSS Export Volume Flow Curves= 0
DXF OffsetX= 0
DXF OffsetY= 0
DXF ScaleX= 0
DXF ScaleY= 0

--- MIDDLEILCK.p01 (plan) ---

Plan Title=Floodplain
Program Version=4.00
Geom File=g01
Flow File=f01
K Sum by GR=0
Std Step Tol=0.01
Critical Tol=0.01
Num of Std Step Trials=20
Max Error Tol=0.3
Flow Tol Ratio=0.001
Split Flow NTrial=30
Split Flow Tol=0.02
Split Flow Ratio=0.02
Log Output Level=0
Friction Slope Method=1
Unsteady Friction Slope Method=2
Unsteady Bridges Friction Slope Method=1
Global Log Level=0
CheckData=False
Run HTab=0
Run UNet=0
Run PostProcess=0
UNET Theta=0
UNET Theta Warmup=0
UNET ZTol=0
UNET ZSATol=0
UNET MxIter=0
UNET MaxInSteps=0
UNET DtIC=0
UNET DtMin=0
UNET MaxCRTS=0
UNET WFStab=0
UNET SFStab=0
UNET WFX=0
UNET SFX=0
UNET DSS MLevel=0
UNET DZMax Abort=0
UNET Convert EG Bridges=0
UNET Use Existing IB Tables=0
UNET Froude Limit=0
UNET Froude Power=0
Write IC File=0
Echo Input=False
Echo Output=False
Write Detailed=0

--- MIDDLEILCK.f01 (steady flow) ---

Flow Title=NFF Regression Equation
Program Version=4.00
Number of Profiles=1
Profile Names=P100yr
River Rch & RM=MIDDLEILCK,Main      ,14734.1
915.4482
River Rch & RM=MIDDLEILCK,Main      ,12761.2
962.1133
River Rch & RM=MIDDLEILCK,Main      ,10750.4
1066.081
River Rch & RM=MIDDLEILCK,Main      ,6215.2
1181.064
River Rch & RM=MIDDLEILCK,Main      ,5951
1347.762
River Rch & RM=MIDDLEILCK,Main      ,4382.2
1372.141
River Rch & RM=MIDDLEILCK,Main      ,73.2
1523.526
Boundary for River Rch & Prof#=MIDDLEILCK,Main      ,1
Up Type=0
Dn Type=3
Dn Slope=0.018624

--- MIDDLEILCK.g01 (geometry) ---

Geom Title=USGS 10m DEM
Program Version=4.10

River Reach=MIDDLEILCK      ,Main
Reach XY= 30
       1690730.3      269670.972     1690750.367      269996.671
     1690357.359      270840.757     1690075.916      271124.517
     1689766.675      271249.603     1689347.383      271624.943
     1689098.092      271742.425     1688935.086      271997.802
     1688581.834      272176.166      1688481.07      272391.591
     1688318.921      272471.507     1688335.136       272579.22
     1687892.703      273413.126     1687889.228      273667.931
     1687708.548      273808.074     1687728.448      274309.152
       1687526.3      274465.267     1687541.767      275017.238
     1687347.189      275992.445     1686704.386      276718.638
     1686177.404      276957.228     1685835.734      277403.136
     1685202.197      277575.708     1684672.898      278074.894
     1684486.427      278092.267     1684302.273      278218.511
     1684024.304      278816.144     1683386.134      279762.396
     1682845.254      280283.587     1682702.795      280329.915

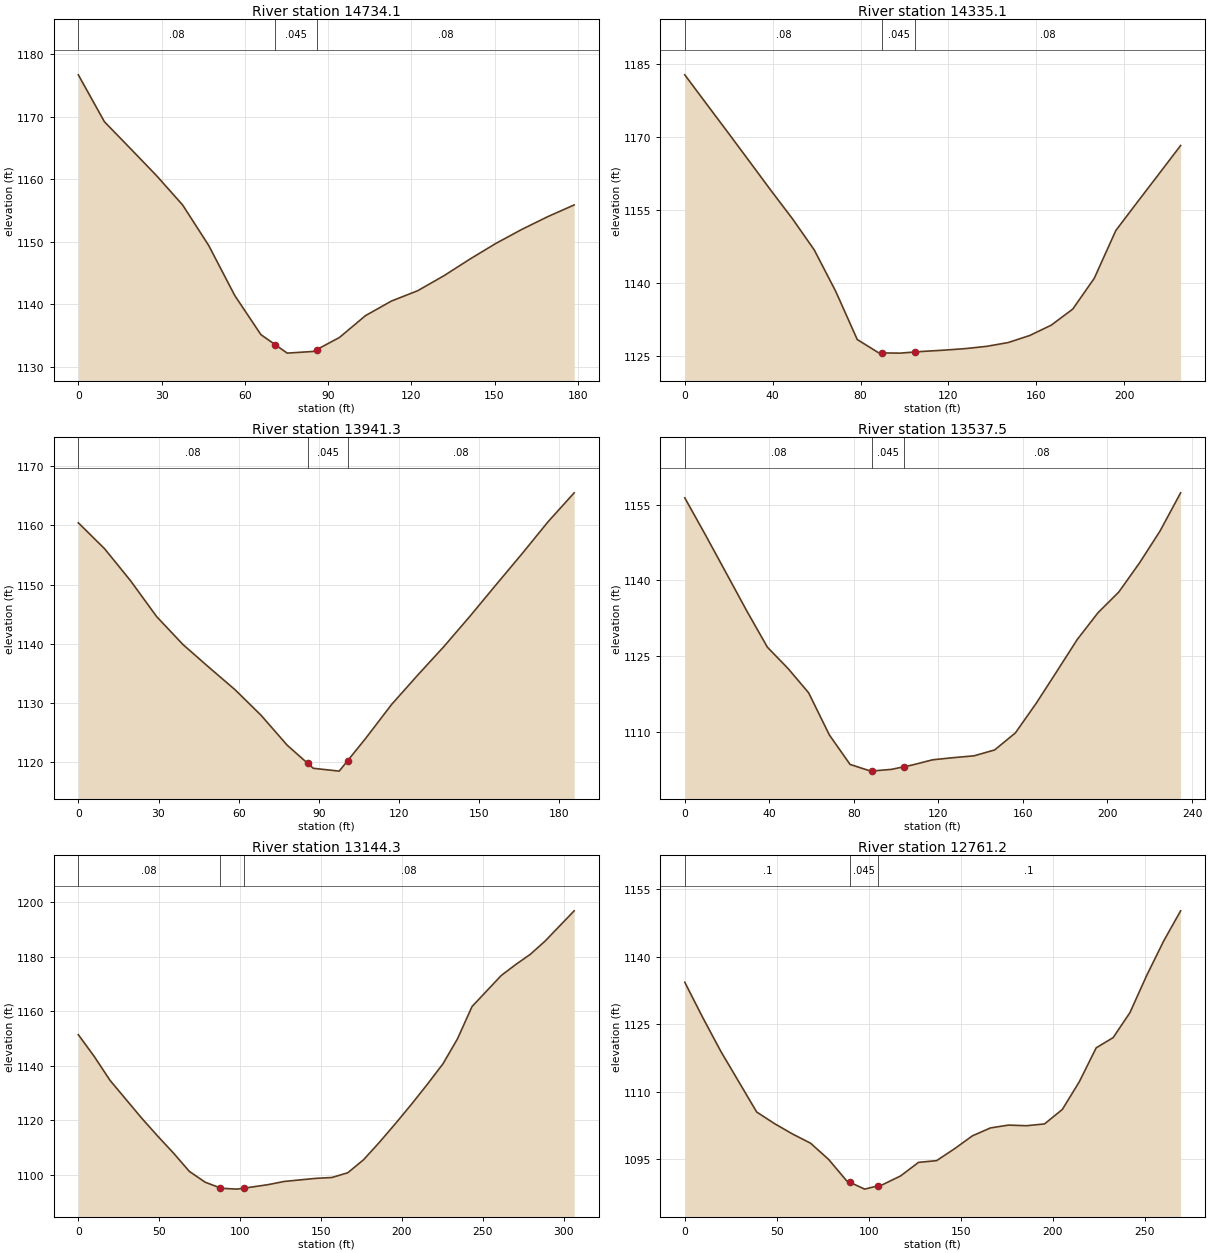
Type RM Length L Ch R = 1 ,14734.1 ,388.8,398.7,408.5
XS GIS Cut Line= 2
      1690654.22      269692.897     1690830.842      269665.491
#Sta/Elev= 22
       0 1176.71     9.4 1169.21    18.8 1164.91    28.2 1160.58    37.6 1155.89
      47 1149.41    56.4  1141.4    65.8 1135.16      71 1133.54    75.3  1132.2
    84.7 1132.47      86 1132.78    94.1  1134.7   103.5  1138.2   112.9 1140.54
   122.3 1142.18   131.7 1144.56   141.1 1147.23   150.5 1149.75   159.9    1152
   169.3 1154.05   178.7  1155.9
#Mann= 3 , 0 , 0
       0     .08       0      71    .045       0      86     .08       0
Bank Sta=71,86
XS Rating Curve= 0 ,0
Exp/Cntr=0.3,0.1

Type RM Length L Ch R = 1 ,14335.1 ,388.7,393.5,398.2
XS GIS Cut Line= 2
     1690623.429      270040.839      1690840.09      270103.956
#Sta/Elev= 26
       0 1182.72     9.8 1176.81    19.6 1170.93    29.4 1164.99    39.2 1159.03
    49.1 1153.16    58.9 1146.85    68.7 1138.34    78.5 1128.46    88.3 1125.72
    89.9 1125.71    98.1 1125.67   104.9 1125.91   107.9 1126.01   117.7 1126.27
   127.6 1126.59   137.4 1127.06   147.2 1127.84     157 1129.28   166.8  1131.4
   176.6  1134.7   186.4 1141.02   196.2  1150.8     206 1156.62   215.9 1162.44
   225.7 1168.23
#Mann= 3 , 0 , 0
       0     .08       0    89.9    .045       0   104.9     .08       0
Bank Sta=89.9,104.9
XS Rating Curve= 0 ,0
Exp/Cntr=0.3,0.1

Type RM Length L Ch R = 1 ,13941.3 ,407.8,403.5,414.1
XS GIS Cut Line= 2
     1690459.822      270375.765      1690623.44      270463.221
#Sta/Elev= 22
       0 1160.45     9.8 1156.08    19.5 1150.68    29.3 1144.59    39.1 1139.89
    48.8 1136.04    58.6 1132.24    68.4 1127.89    78.1 1122.86    85.8 1119.78
    87.9 1118.94    97.6 1118.46   100.8 1120.25   107.4 1123.94   117.2 1129.73
   126.9 1134.66   136.7 1139.49   146.5 1144.64   156.2 1149.93     166 1155.22
   175.8 1160.66   185.5 1165.52
#Mann= 3 , 0 , 0
       0     .08       0    85.8    .045       0   100.8     .08       0
Bank Sta=85.8,100.8
XS Rating Curve= 0 ,0
Exp/Cntr=0.3,0.1

Type RM Length L Ch R = 1 ,13537.5 ,395.4,393.2,391
XS GIS Cut Line= 2
     1690311.967       270733.28     1690501.756      270871.201
#Sta/Elev= 27
       0 1156.34     9.8 1148.97    19.6 1141.43    29.3 1133.94    39.1 1126.72
    48.9 1122.48    58.6 1117.68    68.4 1109.33    78.2 1103.48      88 1102.15
    88.5 1102.17    97.8  1102.5   103.5    1103   107.5 1103.35   117.3  1104.4
   127.1 1104.82   136.9 1105.19   146.6 1106.35   156.4 1109.72   166.2 1115.56
     176 1121.91   185.7 1128.26   195.5 1133.56   205.3 1137.64   215.1 1143.41
   224.8 1149.72   234.6 1157.34
#Mann= 3 , 0 , 0
       0     .08       0    88.5    .045       0   103.5     .08       0
Bank Sta=88.5,103.5
XS Rating Curve= 0 ,0
Exp/Cntr=0.3,0.1

Type RM Length L Ch R = 1 ,13144.3 ,369.2,383.1,397
XS GIS Cut Line= 3
     1690039.534      271017.269     1690233.698      271131.483
     1690303.613      271172.609
#Sta/Elev= 30
       0 1151.42     9.8 1143.44    19.6 1134.63    39.2 1120.72      49 1114.19
    58.8 1107.93    68.6  1101.2    78.4 1097.22    87.5 1095.16    88.2    1095
    97.9 1094.68   102.5 1095.04   117.5 1096.35   127.3 1097.51   146.9 1098.64
   156.7 1098.95   166.5 1100.69   176.3  1105.5   186.1 1111.91   195.9  1118.7
   205.7 1125.73   215.5 1133.05   225.3 1140.68   234.3 1149.88   243.3 1161.76
   261.3 1173.13   270.3 1177.19   279.3 1180.93   288.4 1185.77   306.4 1196.91
#Mann= 3 , 0 , 0
       0     .08       0    87.5    .045       0   102.5     .08       0
Bank Sta=87.5,102.5
XS Rating Curve= 0 ,0
Exp/Cntr=0.3,0.1

Type RM Length L Ch R = 1 ,12761.2 ,440.8,429.4,418
XS GIS Cut Line= 3
     1689751.134      271152.035     1689835.875      271339.063
     1689862.382      271397.564
#Sta/Elev= 30
       0 1134.32     9.8 1126.47    19.6 1118.99    39.1 1105.53    48.9 1102.93
    58.7 1100.63    68.4 1098.61    78.2 1095.02      88 1090.27    89.8 1089.93
    97.8 1088.42   104.8 1089.13   107.6 1089.42   117.3 1091.34   127.1 1094.36
   136.9 1094.74   146.7 1097.39   156.4 1100.25   166.2    1102     176 1102.63
   185.8 1102.49   195.6 1102.89   205.3 1106.11   214.5 1112.24   223.7 1119.78
   232.9 1122.04     242 1127.56   251.2 1135.88   260.4 1143.49   269.6 1150.18
#Mann= 3 , 0 , 0
       0      .1       0    89.8    .045       0   104.8      .1       0
Bank Sta=89.8,104.8
XS Rating Curve= 0 ,0
Exp/Cntr=0.3,0.1

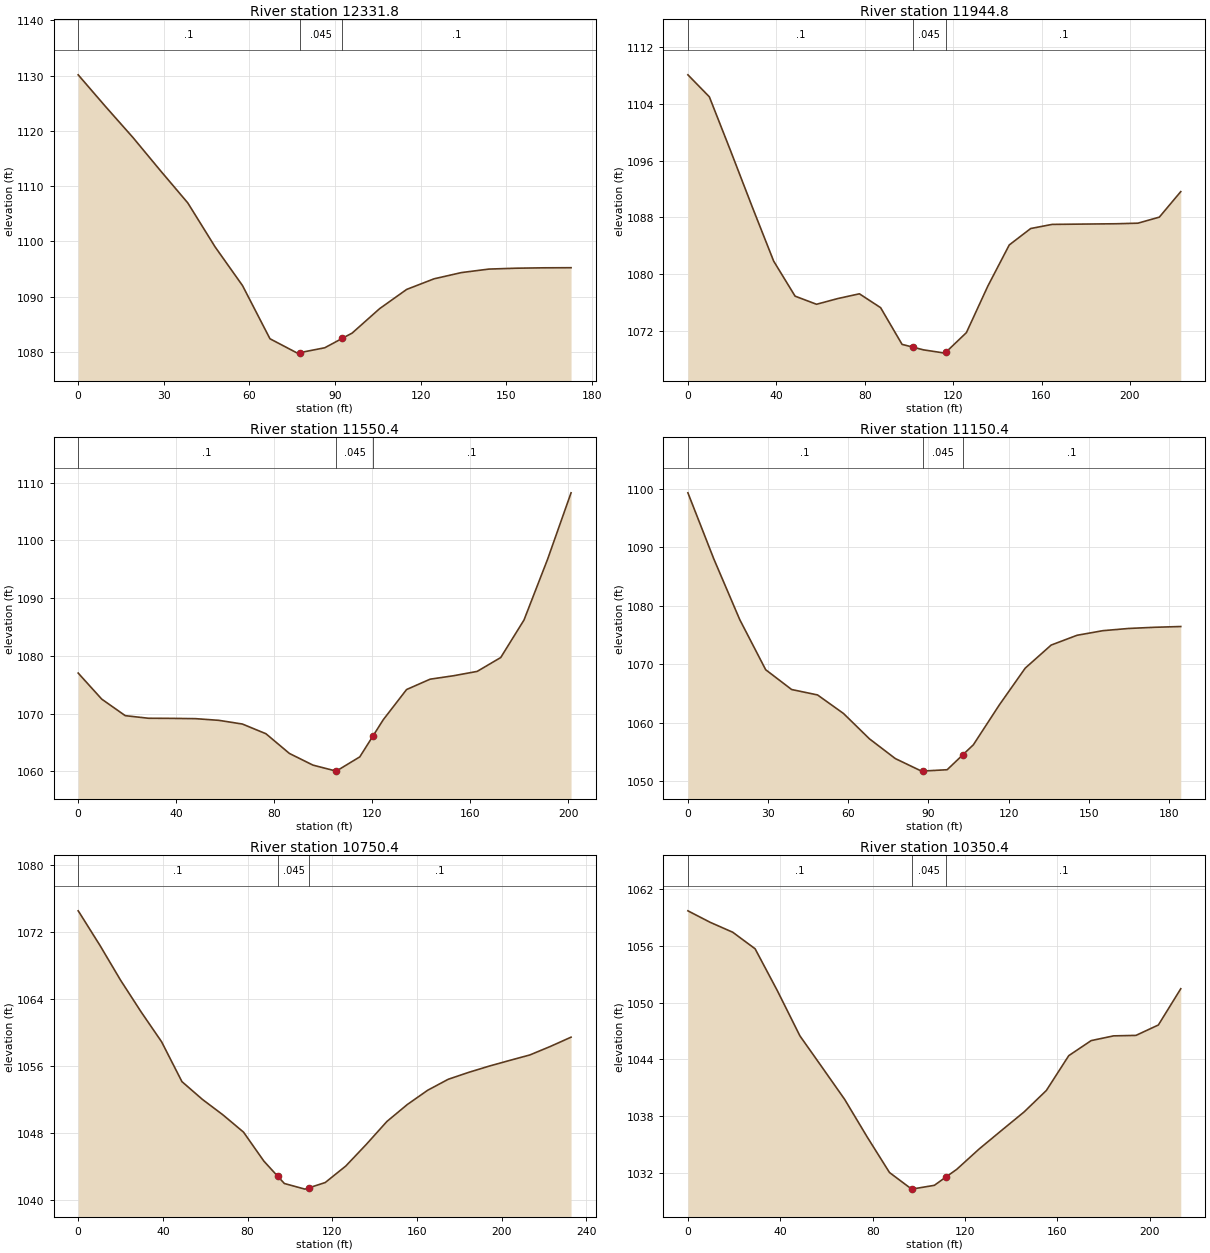
Type RM Length L Ch R = 1 ,12331.8 ,377.5,386.9,396.3
XS GIS Cut Line= 2
     1689379.189      271440.482     1689517.779      271543.554
#Sta/Elev= 21
       0 1130.15     9.6  1124.4    19.2  1118.8    28.8 1112.82    38.4 1106.97
      48 1098.99    57.6 1091.99    67.2 1082.38    76.8 1079.78    77.6 1079.86
    86.4 1080.75    92.6 1082.47      96 1083.41   105.6 1087.82   115.1 1091.31
   124.7 1093.23   134.3 1094.36   143.9 1094.99   153.5 1095.15   163.1 1095.22
   172.7 1095.24
#Mann= 3 , 0 , 0
       0      .1       0    77.6    .045       0    92.6      .1       0
Bank Sta=77.6,92.6
XS Rating Curve= 0 ,0
Exp/Cntr=0.3,0.1

Type RM Length L Ch R = 1 ,11944.8 ,398.9,393.3,387.8
XS GIS Cut Line= 2
     1689094.583      271617.051     1689204.549      271811.021
#Sta/Elev= 26
       0 1108.06     9.7 1104.97    19.4 1097.31    29.1  1089.5    38.8 1081.87
    48.5 1076.94    58.2  1075.8    67.9 1076.61    77.6 1077.27    87.2 1075.32
    96.9 1070.16   101.7 1069.78   106.6 1069.39   116.3 1068.93   116.7 1069.05
     126 1071.81   135.7 1078.35   145.4 1084.14   155.1 1086.45   164.8 1087.03
   174.5 1087.06   184.2 1087.09   193.9 1087.12   203.6  1087.2   213.3 1088.05
     223 1091.64
#Mann= 3 , 0 , 0
       0      .1       0   101.7    .045       0   116.7      .1       0
Bank Sta=101.7,116.7
XS Rating Curve= 0 ,0
Exp/Cntr=0.3,0.1

Type RM Length L Ch R = 1 ,11550.4 ,407.5,399.9,392.3
XS GIS Cut Line= 2
     1688839.223      271932.496     1688976.129      272079.771
#Sta/Elev= 23
       0 1077.03     9.6 1072.52    19.2 1069.65    28.7  1069.2    38.3 1069.18
    47.9 1069.13    57.4 1068.84      67  1068.2    76.6 1066.52    86.2  1063.1
    95.8 1061.08   105.3 1060.04   114.9 1062.51   120.3 1066.14   124.5 1068.96
     134 1074.18   143.6 1075.97   153.2 1076.57   162.8 1077.32   172.4 1079.72
   181.9 1086.22   191.5 1096.72   201.1 1108.26
#Mann= 3 , 0 , 0
       0      .1       0   105.3    .045       0   120.3      .1       0
Bank Sta=105.3,120.3
XS Rating Curve= 0 ,0
Exp/Cntr=0.3,0.1

Type RM Length L Ch R = 1 ,11150.4 ,396.5,399.3,401.2
XS GIS Cut Line= 2
     1688489.792      272149.677     1688651.488      272238.316
#Sta/Elev= 22
       0 1099.35     9.7 1088.02    19.4 1077.63    29.1 1069.05    38.8 1065.66
    48.5 1064.73    58.2 1061.56    67.9 1057.22    77.6 1053.83    87.4 1051.68
    87.8 1051.69      97 1051.92   102.8 1054.45   106.8 1056.19   116.5 1063.01
   126.2 1069.32   135.9 1073.27   145.6 1074.95   155.3 1075.74     165 1076.12
   174.7 1076.32   184.4 1076.45
#Mann= 3 , 0 , 0
       0      .1       0    87.8    .045       0   102.8      .1       0
Bank Sta=87.8,102.8
XS Rating Curve= 0 ,0
Exp/Cntr=0.3,0.1

Type RM Length L Ch R = 1 ,10750.4 ,403.6,399.7,395.7
XS GIS Cut Line= 3
     1688249.057      272394.563     1688249.622      272394.967
     1688438.475       272529.86
#Sta/Elev= 28
       0 1074.51      .7 1074.24    10.4 1070.33      20 1066.23    29.7 1062.44
    39.4 1058.86      49  1054.1    58.7 1051.97    68.4 1050.12    78.1 1048.06
    87.7  1044.6    94.2  1042.8    97.4 1041.92   107.1 1041.25   109.2 1041.42
   116.7 1042.04   126.4 1044.01   136.1  1046.6   145.8 1049.33   155.4 1051.35
   165.1 1053.07   174.8 1054.38   184.4  1055.2   194.1 1055.95   203.8 1056.63
   213.4 1057.29   223.1 1058.31   232.8 1059.41
#Mann= 3 , 0 , 0
       0      .1       0    94.2    .045       0   109.2      .1       0
Bank Sta=94.2,109.2
XS Rating Curve= 0 ,0
Exp/Cntr=0.3,0.1

Type RM Length L Ch R = 1 ,10350.4 ,399.5,399.8,399.8
XS GIS Cut Line= 2
     1688092.955      272751.366     1688285.241       272843.99
#Sta/Elev= 24
       0  1059.7     9.7 1058.48    19.4 1057.44    29.1 1055.69    38.8 1051.23
    48.5 1046.49    58.2 1043.14    67.9 1039.77    77.6 1035.82    87.3 1032.05
    96.9  1030.3   106.7  1030.7   111.9 1031.61   116.4 1032.39   126.1 1034.54
   135.8  1036.5   145.5 1038.44   155.2 1040.72   164.9  1044.4   174.6 1045.99
   184.3 1046.49     194 1046.54   203.7 1047.64   213.4 1051.47
#Mann= 3 , 0 , 0
       0      .1       0    96.9    .045       0   111.9      .1       0
Bank Sta=96.9,111.9
XS Rating Curve= 0 ,0
Exp/Cntr=0.3,0.1

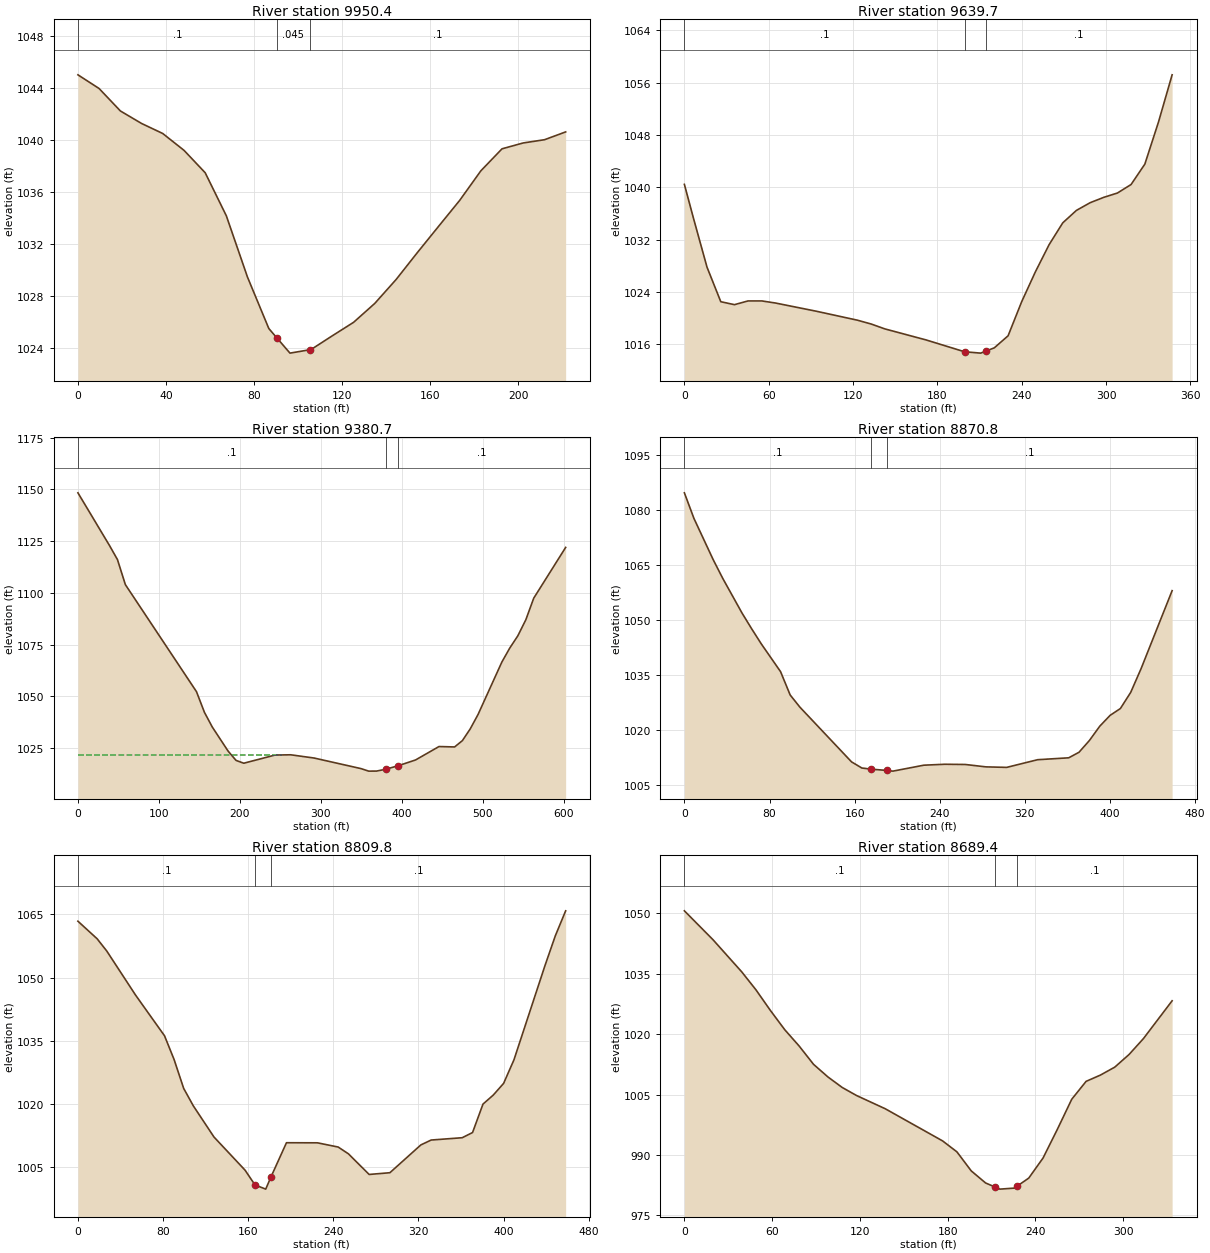
Type RM Length L Ch R = 1 ,9950.4  ,316.8,310.6,304.3
XS GIS Cut Line= 2
     1687964.735      273111.152     1688156.547      273221.949
#Sta/Elev= 26
       0 1045.02     9.6 1043.97    19.3 1042.24    28.9 1041.28    38.5 1040.51
    48.2 1039.21    57.8 1037.49    67.4 1034.18      77 1029.47    86.7 1025.51
    90.3  1024.8    96.3 1023.62   105.3 1023.88   105.9  1023.9   115.6 1024.96
   125.2 1025.99   134.8 1027.44   144.5 1029.28   154.1 1031.34   163.7 1033.35
   173.4 1035.37     183 1037.64   192.6 1039.33   202.2 1039.78   211.9 1040.03
   221.5 1040.63
#Mann= 3 , 0 , 0
       0      .1       0    90.3    .045       0   105.3      .1       0
Bank Sta=90.3,105.3
XS Rating Curve= 0 ,0
Exp/Cntr=0.3,0.1

Type RM Length L Ch R = 1 ,9639.7  ,260,258.7,257.6
XS GIS Cut Line= 3
     1687691.317      273368.543      1687697.52      273370.124
     1688027.619      273454.261
#Sta/Elev= 30
       0 1040.44     6.4 1035.31    16.1 1027.78    25.9  1022.5    35.6 1022.05
    45.3 1022.62    55.1 1022.62    64.8  1022.3      94 1021.04   123.2 1019.67
   132.9 1019.09   142.7 1018.34   171.9 1016.66   199.3 1014.85   210.8 1014.64
   214.3 1014.93   220.5 1015.45   230.3 1017.29     240 1022.52   249.7 1027.06
   259.5 1031.23   269.2 1034.56   278.9 1036.46   288.7 1037.64   298.4 1038.46
   308.1 1039.12   317.8 1040.42   327.6 1043.54   337.3 1049.97     347 1057.19
#Mann= 3 , 0 , 0
       0      .1       0   199.3    .045       0   214.3      .1       0
Bank Sta=199.3,214.3
XS Rating Curve= 0 ,0
Exp/Cntr=0.3,0.1

Type RM Length L Ch R = 1 ,9380.7  ,511.3,509.4,507.3
XS GIS Cut Line= 4
     1687504.438      273600.845     1687695.847      273639.168
     1687988.803      273697.822     1688094.916      273719.068
#Sta/Elev= 30
       0 1148.33      39 1122.86    48.8 1116.08    58.6 1103.95   146.4 1052.23
   156.2 1042.26   165.9 1035.15   185.4 1023.54   195.2 1019.03   204.8 1017.66
   243.4 1021.61   262.7 1021.73   291.6 1020.17   349.4 1015.07     359 1013.84
   368.7 1013.86   380.3 1014.78   395.3 1016.43   416.9 1019.24   445.8 1025.72
   465.1 1025.52   474.7 1028.58   484.3  1034.2     494 1041.18   523.5  1066.6
   533.3 1073.38   543.2 1079.26     553 1086.95   562.8 1097.43   602.2 1121.95
#Mann= 3 , 0 , 0
       0      .1       0   380.3    .045       0   395.3      .1       0
#XS Ineff= 2 , 0
          252.49 1021.78
Permanent Ineff=
       F       F
Bank Sta=380.3,395.3
XS Rating Curve= 0 ,0
Exp/Cntr=0.3,0.1

Type RM Length L Ch R = 1 ,8870.8  ,63.7,61.1,58.5
XS GIS Cut Line= 3
     1687510.828      274068.709     1687618.678      274080.386
     1687966.587      274118.053
#Sta/Elev= 30
       0 1084.58       9 1077.59    27.1 1066.35    36.2 1061.19    54.2 1051.81
    63.3  1047.5    72.3 1043.41    90.4 1035.85    99.4 1029.51   108.5  1026.2
   157.1 1011.27   166.8  1009.6   175.7 1009.28   190.7 1008.93     196 1008.75
   225.1 1010.37   244.6 1010.62     264 1010.56   283.4 1009.91   302.9 1009.77
     332 1011.86   361.2 1012.38   370.9 1013.89   380.7 1017.11   390.4 1020.99
   400.1 1023.94   409.8 1025.81   419.5 1030.22   429.3 1036.72   458.4 1057.92
#Mann= 3 , 0 , 0
       0      .1       0   175.7    .045       0   190.7      .1       0
Bank Sta=175.7,190.7
XS Rating Curve= 0 ,0
Exp/Cntr=0.3,0.1

Type RM Length L Ch R = 1 ,8809.8  ,109.7,120,128.5
XS GIS Cut Line= 3
     1687524.423      274149.738     1687632.902       274149.36
     1687982.842       274148.14
#Sta/Elev= 30
       0 1063.38    18.1  1059.2    27.1 1056.31    54.2 1045.85    81.4 1036.21
    90.4 1030.57    99.4 1023.73   108.5 1019.58   127.9  1012.2   157.1 1004.34
   166.4 1000.85   176.5  999.85   181.4 1002.72     196 1010.85   225.1 1010.83
   244.6 1009.83   254.3 1008.21   273.7 1003.33   293.2 1003.74   322.3 1010.33
     332 1011.49   361.2 1012.04   370.9 1013.27   380.7 1020.01   390.4 1022.16
   400.1 1024.93   409.8  1030.5     439 1052.88   448.7 1059.92   458.4 1065.84
#Mann= 3 , 0 , 0
       0      .1       0   166.4    .045       0   181.4      .1       0
Bank Sta=166.4,181.4
XS Rating Curve= 0 ,0
Exp/Cntr=0.3,0.1

Type RM Length L Ch R = 1 ,8689.4  ,385.7,380.9,376.1
XS GIS Cut Line= 2
     1687545.024      274166.149     1687860.272      274274.701
#Sta/Elev= 30
       0 1050.61    19.6 1043.42    39.2 1035.46      49 1030.96    58.8 1025.88
    68.6  1021.1    78.4 1017.07    88.3  1012.5    98.1 1009.38   107.9 1006.76
   117.7 1004.76   137.3 1001.48   176.5   993.5   186.3  990.78   196.1  986.05
   205.9  983.06   212.5  982.03   215.7  981.53   225.5  981.78   227.5  982.28
   235.4  984.27   245.2  989.27     255  996.41   264.8 1003.85   274.6 1008.28
   284.4 1009.84   294.2 1011.81     304 1014.96   313.8  1018.9   333.4 1028.28
#Mann= 3 , 0 , 0
       0      .1       0   212.5    .045       0   227.5      .1       0
Bank Sta=212.5,227.5
XS Rating Curve= 0 ,0
Exp/Cntr=0.3,0.1

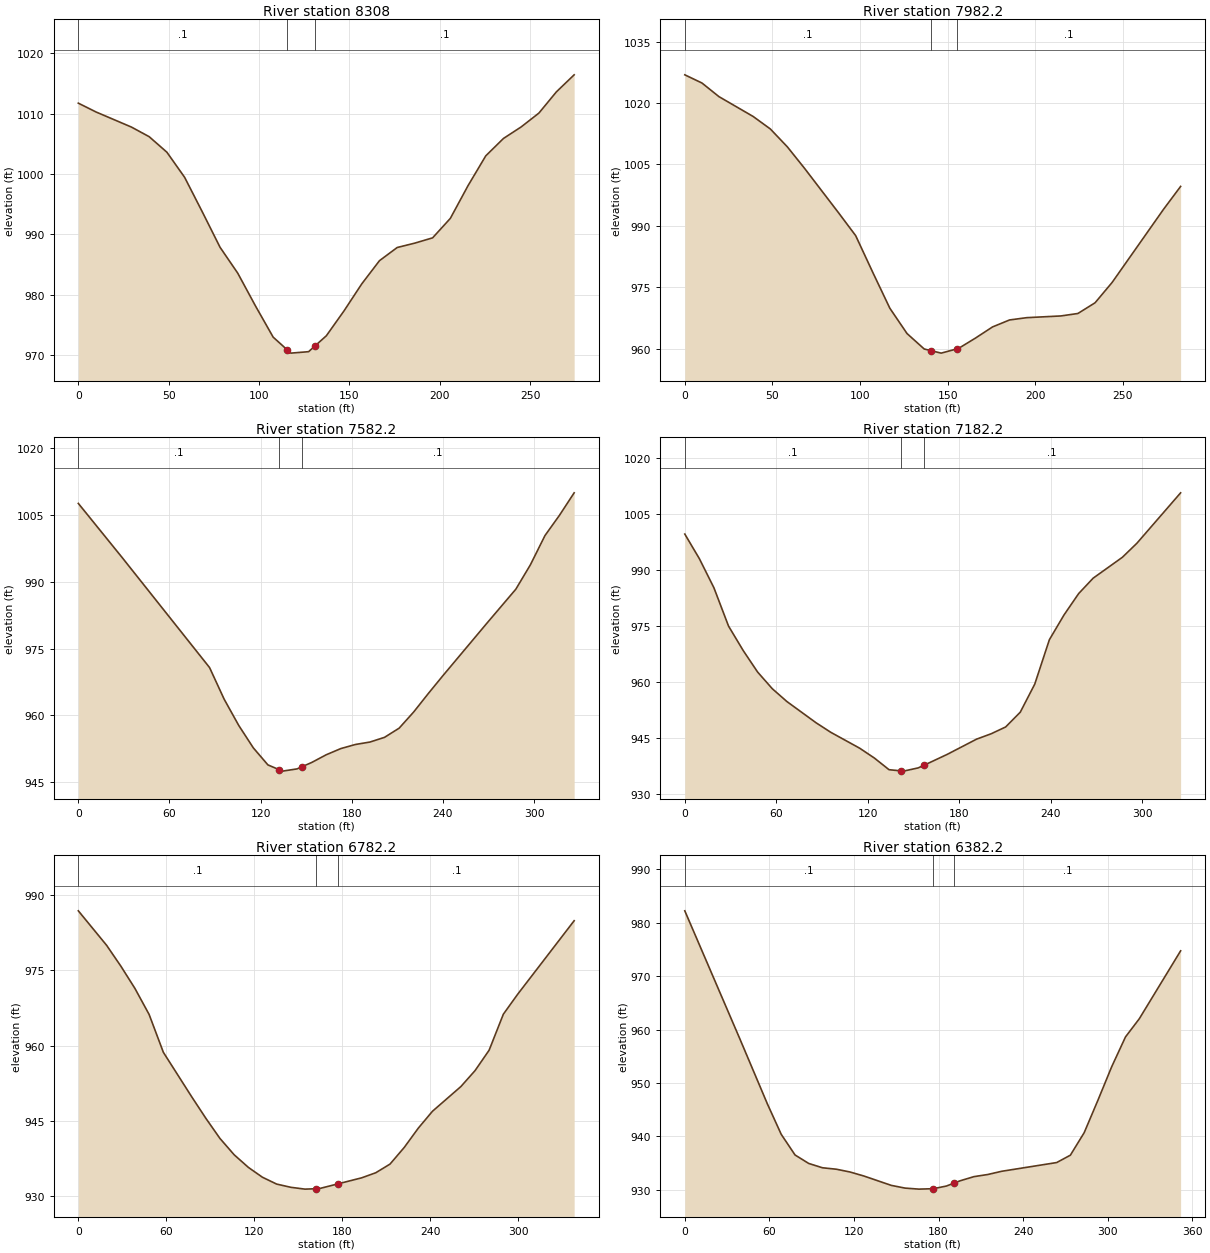
Type RM Length L Ch R = 1 ,8308    ,332.5,325.7,318.9
XS GIS Cut Line= 2
     1687399.684      274487.607     1687671.798      274522.509
#Sta/Elev= 30
       0 1011.72     9.8 1010.26    29.4 1007.76    39.2 1006.17      49  1003.6
    58.8  999.45    68.6  993.72    78.4  987.87    88.2  983.58      98  978.16
   107.8  972.99   115.7  970.86   117.6  970.35   127.4  970.59   130.7  971.48
   137.2  973.22     147  977.35   156.8  981.81   166.6  985.65   176.4  987.83
   186.2  988.56     196  989.43   205.8  992.65   215.6  998.07   225.4    1003
   235.2 1005.88     245 1007.79   254.8 1010.08   264.5  1013.6   274.3 1016.41
#Mann= 3 , 0 , 0
       0      .1       0   115.7    .045       0   130.7      .1       0
Bank Sta=115.7,130.7
XS Rating Curve= 0 ,0
Exp/Cntr=0.3,0.1

Type RM Length L Ch R = 1 ,7982.2  ,389.7,400,410.2
XS GIS Cut Line= 2
     1687393.228       274851.08     1687671.798      274802.013
#Sta/Elev= 27
       0 1026.89     9.8 1024.89    19.5 1021.56      39 1016.72    48.8 1013.67
    58.5 1009.31    68.3 1004.07    87.8  993.16    97.5  987.62   107.3  978.61
     117  969.89   126.8  963.71   136.6  959.94   140.3  959.55   146.3  958.93
   155.3  959.97   156.1  960.06   165.8  962.59   175.6  965.33   185.3  967.03
   195.1  967.59   214.6  968.01   224.3  968.61   234.1  971.23   243.8  976.18
   273.1  994.02   282.9  999.64
#Mann= 3 , 0 , 0
       0      .1       0   140.3    .045       0   155.3      .1       0
Bank Sta=140.3,155.3
XS Rating Curve= 0 ,0
Exp/Cntr=0.3,0.1

Type RM Length L Ch R = 1 ,7582.2  ,397.5,399.9,402.3
XS GIS Cut Line= 2
     1687358.223        275179.6     1687671.798      275270.371
#Sta/Elev= 27
       0 1007.63    28.8  995.48    86.4  970.72      96  963.61   105.6  957.71
   115.2  952.67   124.8  948.84   132.3  947.75   134.4  947.44     144  947.94
   147.3  948.44   153.6  949.38   163.2  951.12   172.8  952.51   182.4  953.43
     192  953.98   201.6  955.04   211.2   957.1   220.8  960.75   230.4  964.89
     240   968.9   268.8  980.63     288  988.34   297.6  993.83   307.2 1000.41
   316.8 1004.99   326.4 1010.01
#Mann= 3 , 0 , 0
       0      .1       0   132.3    .045       0   147.3      .1       0
Bank Sta=132.3,147.3
XS Rating Curve= 0 ,0
Exp/Cntr=0.3,0.1

Type RM Length L Ch R = 1 ,7182.2  ,398.2,399.8,402
XS GIS Cut Line= 2
     1687281.796      275553.301     1687583.173       275675.85
#Sta/Elev= 30
       0  999.57     9.6  992.97    19.1  985.23    28.7  974.98    38.3  968.46
    47.8  962.69    57.4  958.25      67  954.82    86.1  949.16    95.7  946.62
   114.8  942.34   124.4  939.72     134  936.61   141.7   936.3   143.5  936.23
   153.1  937.09   156.7  937.75   172.2  940.71   191.4  944.77     201  946.21
   210.5  948.03   220.1  951.98   229.6  959.48   239.2  971.35   248.8  977.96
   258.4  983.67   267.9  987.78   287.1  993.37   296.6  997.11   325.3 1010.59
#Mann= 3 , 0 , 0
       0      .1       0   141.7    .045       0   156.7      .1       0
Bank Sta=141.7,156.7
XS Rating Curve= 0 ,0
Exp/Cntr=0.3,0.1

Type RM Length L Ch R = 1 ,6782.2  ,392.6,399.5,409.3
XS GIS Cut Line= 2
     1687195.955      275913.994     1687495.237      276071.563
#Sta/Elev= 30
       0   986.8    19.3  979.94      29   975.8    38.6  971.37    48.3  966.18
      58  958.66    77.3  949.83      87  945.53    96.6  941.53   106.3  938.28
     116  935.77   125.6  933.81   135.3  932.45     145  931.81   154.6  931.45
   162.4  931.53   164.3  931.55   177.4  932.52   193.3   933.7   202.9  934.71
   212.6  936.43   222.3  939.74   231.9  943.58   241.6  946.95   260.9  951.84
   270.6  955.02   280.2  959.08   289.9  966.24   299.6  970.18   338.2  984.83
#Mann= 3 , 0 , 0
       0      .1       0   162.4    .045       0   177.4      .1       0
Bank Sta=162.4,177.4
XS Rating Curve= 0 ,0
Exp/Cntr=0.3,0.1

Type RM Length L Ch R = 1 ,6382.2  ,148.1,166.8,150.3
XS GIS Cut Line= 2
      1686998.72      276143.041     1687220.408      276416.037
#Sta/Elev= 28
       0  982.25    39.1  958.23    58.6  946.06    68.4  940.37    78.2   936.5
    87.9  934.91    97.7   934.1   107.5  933.83   117.2  933.31     127  932.56
   146.5   930.8   156.3  930.29   166.1   930.1   176.3  930.18   185.6  930.68
   191.3  931.26   195.4  931.67   205.1  932.44   214.9  932.84   224.7  933.44
   263.8  935.08   273.5  936.46   283.3  940.68   293.1  946.79   302.8  953.03
   312.6  958.62   322.4  962.03   351.7  974.75
#Mann= 3 , 0 , 0
       0      .1       0   176.3    .045       0   191.3      .1       0
Bank Sta=176.3,191.3
XS Rating Curve= 0 ,0
Exp/Cntr=0.3,0.1

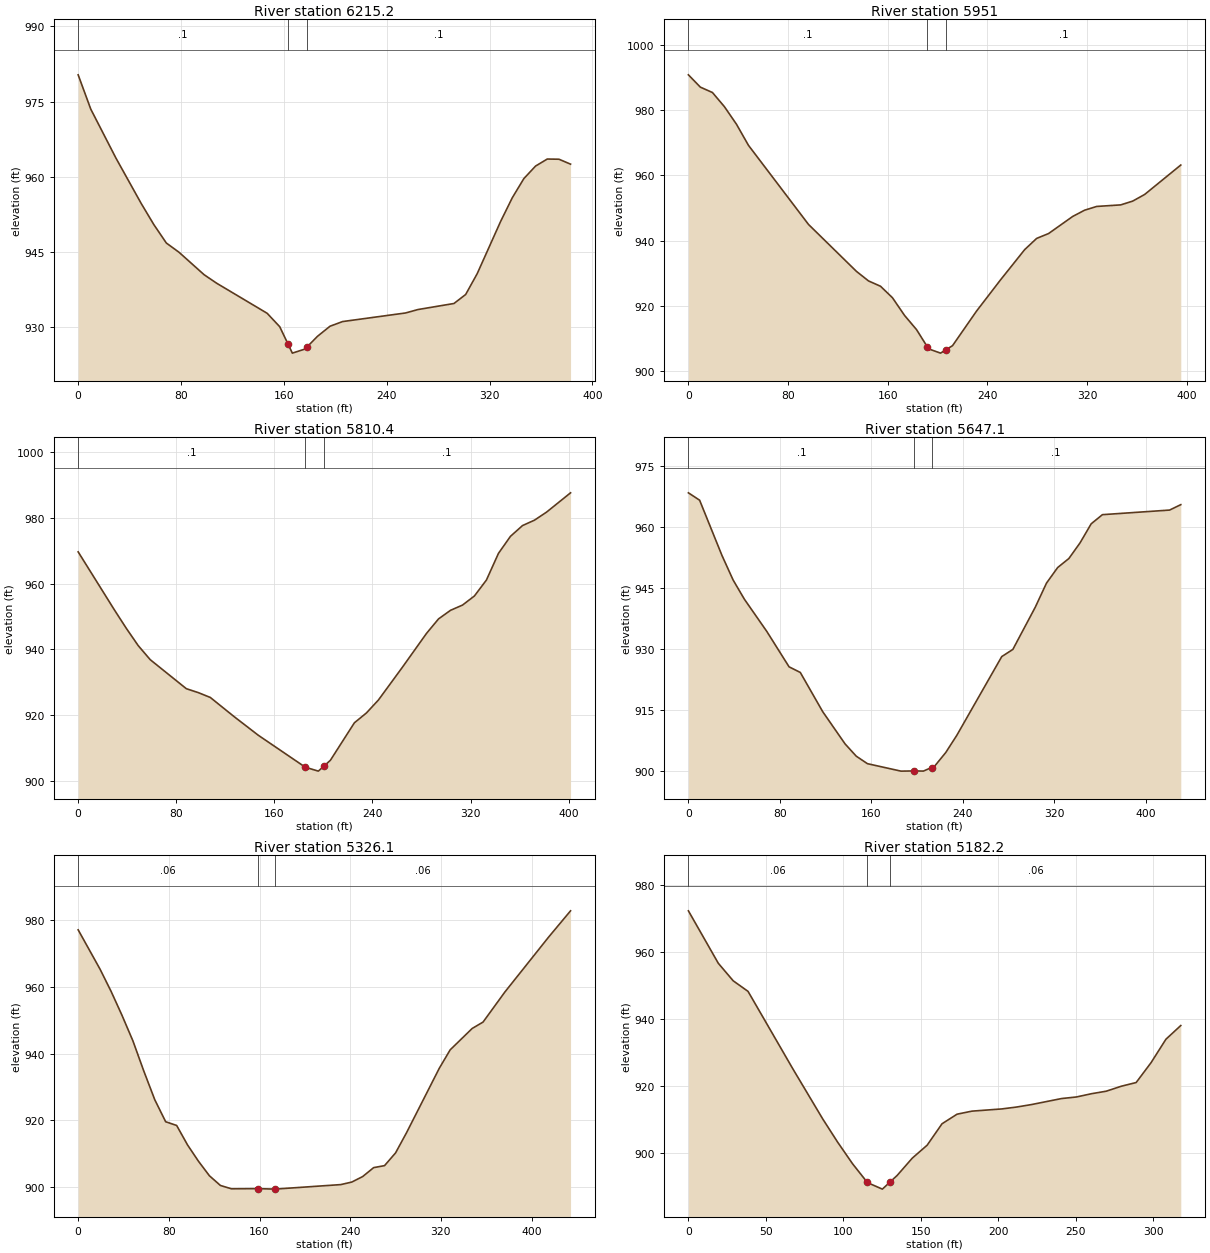
Type RM Length L Ch R = 1 ,6215.2  ,257.8,264.1,277
XS GIS Cut Line= 4
     1686896.959      276237.054     1687002.576      276352.963
     1687118.656       276370.08     1687190.087      276452.274
#Sta/Elev= 30
       0  980.34     9.8  973.51    29.4  963.74      49  954.72    58.8  950.52
    68.6  946.82    78.4  944.99      98   940.5   107.8   938.8     147  932.82
   156.8  930.14   163.1  926.76   166.6  924.88   176.4  925.69   178.1  926.13
   186.2  928.24   195.9  930.24   205.7  931.17   254.6  932.88   264.4  933.57
   292.3  934.77   301.4  936.56   310.4  940.72   328.6  951.12   337.7  955.85
   346.7  959.67   355.8  962.16   364.9  963.56     374  963.52     383  962.54
#Mann= 3 , 0 , 0
       0      .1       0   163.1    .045       0   178.1      .1       0
Bank Sta=163.1,178.1
XS Rating Curve= 0 ,0
Exp/Cntr=0.3,0.1

Type RM Length L Ch R = 1 ,5951    ,140.6,140.5,140.5
XS GIS Cut Line= 2
      1686698.01      276422.251     1686996.128      276681.626
#Sta/Elev= 30
       0  990.84     9.6  987.06    19.3  985.41    28.9  981.07    38.6  975.67
    48.2  969.21    96.4  944.93   134.9  930.52   144.6  927.59   154.2  925.96
   163.8  922.43   173.5     917   183.1  912.66   191.8  907.35   192.8  906.74
   202.4  905.44   206.8  906.49     212  907.73   231.3  918.36   250.6  927.96
   269.9   937.2   279.5  940.64   289.1  942.14   308.4  947.37     318   949.3
   327.7  950.45     347  950.93   356.6  952.09   366.2  954.13   395.2  963.16
#Mann= 3 , 0 , 0
       0      .1       0   191.8    .045       0   206.8      .1       0
Bank Sta=191.8,206.8
XS Rating Curve= 0 ,0
Exp/Cntr=0.3,0.1

Type RM Length L Ch R = 1 ,5810.4  ,154.1,163.1,172.2
XS GIS Cut Line= 2
     1686602.705      276524.887     1686905.696      276788.501
#Sta/Elev= 30
       0  969.61    29.4  952.08    39.2  946.43      49  941.13    58.8  936.86
    88.2  928.06      98  926.86   107.8  925.39   127.3  919.54   146.9  913.92
   185.3   904.2   195.9  903.02   200.3  904.49   205.7   906.3   225.3   917.7
   235.1  920.68   244.9  924.62   264.5  934.59   284.1  944.84   293.9  949.24
   303.7  951.86   313.5  953.45   323.2  956.22     333  961.06   342.8  969.15
   352.6  974.33   362.4  977.59   372.2  979.24     382  981.67   401.6  987.54
#Mann= 3 , 0 , 0
       0      .1       0   185.3    .045       0   200.3      .1       0
Bank Sta=185.3,200.3
XS Rating Curve= 0 ,0
Exp/Cntr=0.3,0.1

Type RM Length L Ch R = 1 ,5647.1  ,320.5,320.9,321.4
XS GIS Cut Line= 2
     1686542.154      276575.596      1686732.84      276961.405
#Sta/Elev= 30
       0  968.44     9.8  966.63    29.3  953.07    39.1     947    48.9   942.3
    68.5  934.38      88  925.66    97.8  924.28   117.4  914.64   136.9  906.73
   146.7   903.7   156.5  901.85   185.8  900.02   197.6  900.07   205.4  900.03
   212.6  900.91   215.2  901.23     225  904.61   234.7  908.86   273.9  928.18
   283.6  929.94   303.2  940.32     313  946.24   322.8  950.08   332.6   952.3
   342.3  956.12   352.1  960.83   361.9  963.07   420.6   964.2   430.4  965.53
#Mann= 3 , 0 , 0
       0      .1       0   197.6    .045       0   212.6      .1       0
Bank Sta=197.6,212.6
XS Rating Curve= 0 ,0
Exp/Cntr=0.3,0.1

Type RM Length L Ch R = 1 ,5326.1  ,149.8,144,138.2
XS GIS Cut Line= 2
     1686261.865      276721.581     1686446.389      277114.876
#Sta/Elev= 30
       0   977.2    19.3   965.4      29  958.78    38.6  951.61    48.3  943.89
    57.9  934.84    67.6  926.22    77.2  919.62    86.9   918.5    96.5  912.66
   106.2  907.74   115.8  903.41   125.5   900.5   135.2   899.5   158.5  899.55
   173.5   899.4   231.7  900.76   241.4  901.52     251  903.17   260.7  905.85
   270.3  906.45     280  910.26   289.6  916.26   318.6  935.66   328.2  941.19
   347.6   947.6   357.2  949.52   376.5  958.56   415.1  975.04   434.4   982.9
#Mann= 3 , 0 , 0
       0     .06       0   158.5    .045       0   173.5     .06       0
Bank Sta=158.5,173.5
XS Rating Curve= 0 ,0
Exp/Cntr=0.3,0.1

Type RM Length L Ch R = 1 ,5182.2  ,402.6,399.8,397
XS GIS Cut Line= 2
     1686125.431      276840.795     1686328.914      277084.977
#Sta/Elev= 30
       0  972.31    19.3  956.64    28.9  951.41    38.5  948.24    67.4  925.11
    86.7  910.13    96.3  903.21     106  896.71   115.2  891.33   115.6   891.1
   125.2  889.16   130.2  891.31   134.8  893.28   144.5  898.42   154.1  902.29
   163.7  908.69   173.4  911.55     183  912.46   202.3  913.12   211.9  913.69
   221.5  914.43   240.8  916.22   250.4  916.69   260.1  917.66   269.7  918.42
   279.3  919.89     289  921.01   298.6  926.94   308.2  933.94   317.8  938.04
#Mann= 3 , 0 , 0
       0     .06       0   115.2    .045       0   130.2     .06       0
Bank Sta=115.2,130.2
XS Rating Curve= 0 ,0
Exp/Cntr=0.3,0.1

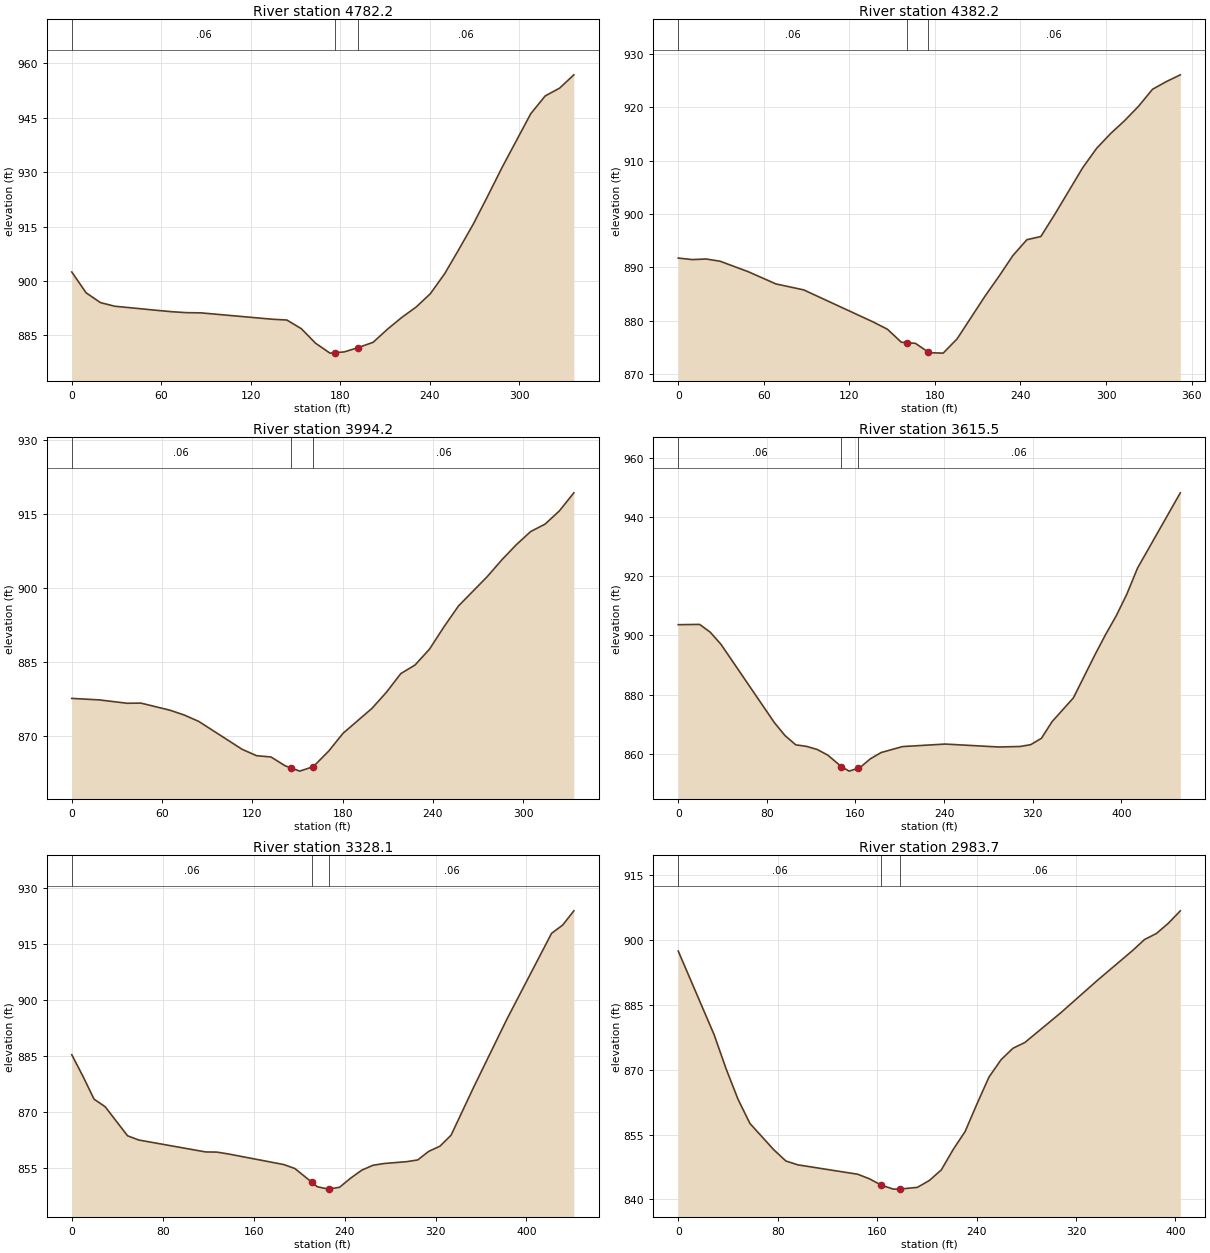
Type RM Length L Ch R = 1 ,4782.2  ,389.6,399.7,409.8
XS GIS Cut Line= 2
     1685840.866      277115.196     1686086.589       277345.21
#Sta/Elev= 30
       0  902.48     9.6  896.75    19.2  894.04    28.8  893.04    57.7  891.88
    67.3  891.52    76.9  891.27    86.6  891.21   134.6  889.45   144.2  889.24
   153.9  886.85   163.5  882.83   173.1  880.12   176.6  880.24   182.7  880.46
   191.6  881.59     202  883.09   211.6  886.69   221.2  889.94   230.8  892.79
   240.4  896.49     250  901.99   259.6  908.75   269.3  915.75   278.9  923.42
   288.5  931.28   307.7  946.06   317.4  950.97     327   953.1   336.6  956.78
#Mann= 3 , 0 , 0
       0     .06       0   176.6    .045       0   191.6     .06       0
Bank Sta=176.6,191.6
XS Rating Curve= 0 ,0
Exp/Cntr=0.3,0.1

Type RM Length L Ch R = 1 ,4382.2  ,388.9,387.9,386.8
XS GIS Cut Line= 2
      1685609.85      277313.987     1685740.212      277641.074
#Sta/Elev= 30
       0  891.75     9.8  891.46    19.6  891.57    29.3  891.16    48.9  889.21
    68.5   886.9      88  885.78   136.9  879.74   146.7   878.4   156.5  875.96
   160.2  875.88   166.3  875.76   175.2  874.15     176     874   185.8  873.92
   195.6  876.61   215.2  884.63     225  888.35   234.7  892.22   244.5  895.19
   254.3  895.79   264.1  899.96   283.6  908.67   293.4  912.32   303.2  915.09
     313  917.51   322.8  920.21   332.6   923.4   342.3  924.84   352.1  926.11
#Mann= 3 , 0 , 0
       0     .06       0   160.2    .045       0   175.2     .06       0
Bank Sta=160.2,175.2
XS Rating Curve= 0 ,0
Exp/Cntr=0.3,0.1

Type RM Length L Ch R = 1 ,3994.2  ,386.5,378.4,370.4
XS GIS Cut Line= 3
     1685230.482      277396.976     1685249.464      277438.929
     1685368.053      277701.032
#Sta/Elev= 30
       0  877.63    18.4  877.32    36.8  876.64      46  876.67    65.2  875.24
    74.8  874.25    84.4  872.96   113.2  867.31   122.8  866.01   132.4  865.75
   141.9  863.95   145.5  863.55   151.5  862.88   160.5  863.78   170.7  866.92
   180.3  870.55   199.5   875.6   209.1  878.86   218.7  882.66   228.2  884.41
   237.8  887.63   247.4  892.15     257  896.36   276.2  902.34   285.8  905.71
   295.4  908.77     305  911.46   314.6  912.97   324.1  915.65   333.7  919.31
#Mann= 3 , 0 , 0
       0     .06       0   145.5    .045       0   160.5     .06       0
Bank Sta=145.5,160.5
XS Rating Curve= 0 ,0
Exp/Cntr=0.3,0.1

Type RM Length L Ch R = 1 ,3615.5  ,283.1,287.6,292.1
XS GIS Cut Line= 2
     1684886.705      277652.215     1685207.211      277972.721
#Sta/Elev= 30
       0  903.64    19.3  903.74    28.9  901.12    38.6  897.02    86.8  870.62
    96.4  866.25   106.1  863.12   115.7  862.61   125.4  861.57     135  859.66
   147.2   855.8   154.3  854.25   162.2  855.21     164  855.43   173.6  858.44
   183.2  860.52   202.5  862.53   241.1  863.38   289.3  862.39   308.6  862.56
   318.2  863.17   327.9  865.32   337.5  870.93   356.8  878.97   376.1   893.4
   385.8   900.3   395.4  906.61     405  913.93   414.7  922.75   453.3  948.12
#Mann= 3 , 0 , 0
       0     .06       0   147.2    .045       0   162.2     .06       0
Bank Sta=147.2,162.2
XS Rating Curve= 0 ,0
Exp/Cntr=0.3,0.1

Type RM Length L Ch R = 1 ,3328.1  ,345.2,343.9,342.6
XS GIS Cut Line= 2
     1684657.596      277766.769     1684903.311      278133.834
#Sta/Elev= 30
       0  885.27     9.8   879.5    19.6  873.35    29.4  871.31    49.1  863.52
    58.9  862.39   117.8  859.19   127.6  859.15   137.4  858.67   186.5  855.81
   196.3  854.74   211.3  851.04     216  849.86   225.8  849.22   226.3  849.25
   235.6  849.72   245.4  852.18   255.2  854.31     265  855.62   274.8  856.09
   294.5  856.58   304.3  857.04   314.1  859.36   323.9  860.73   333.7  863.68
   353.4  876.44   382.8  894.79   422.1   917.8   431.9  920.03   441.7  923.84
#Mann= 3 , 0 , 0
       0     .06       0   211.3    .045       0   226.3     .06       0
Bank Sta=211.3,226.3
XS Rating Curve= 0 ,0
Exp/Cntr=0.3,0.1

Type RM Length L Ch R = 1 ,2983.7  ,172.8,171.8,170.9
XS GIS Cut Line= 2
     1684396.077      277951.754     1684631.208      278280.195
#Sta/Elev= 30
       0  897.49    28.8  878.19    38.5  870.25    48.1   863.2    57.7  857.59
    76.9   851.5    86.6  848.91    96.2  848.02   144.3  845.85   153.9  844.78
   163.5   843.3   173.1   842.4   178.5  842.42   192.4  842.81     202   844.4
   211.6  846.84   221.2  851.57   230.8  855.74   240.4  862.17     250  868.34
   259.7  872.35   269.3     875   278.9  876.34   307.8  883.22   336.6  890.56
   365.5  897.61   375.1  900.16   384.7  901.56   394.3  903.93   403.9   906.8
#Mann= 3 , 0 , 0
       0     .06       0   163.5    .045       0   178.5     .06       0
Bank Sta=163.5,178.5
XS Rating Curve= 0 ,0
Exp/Cntr=0.3,0.1