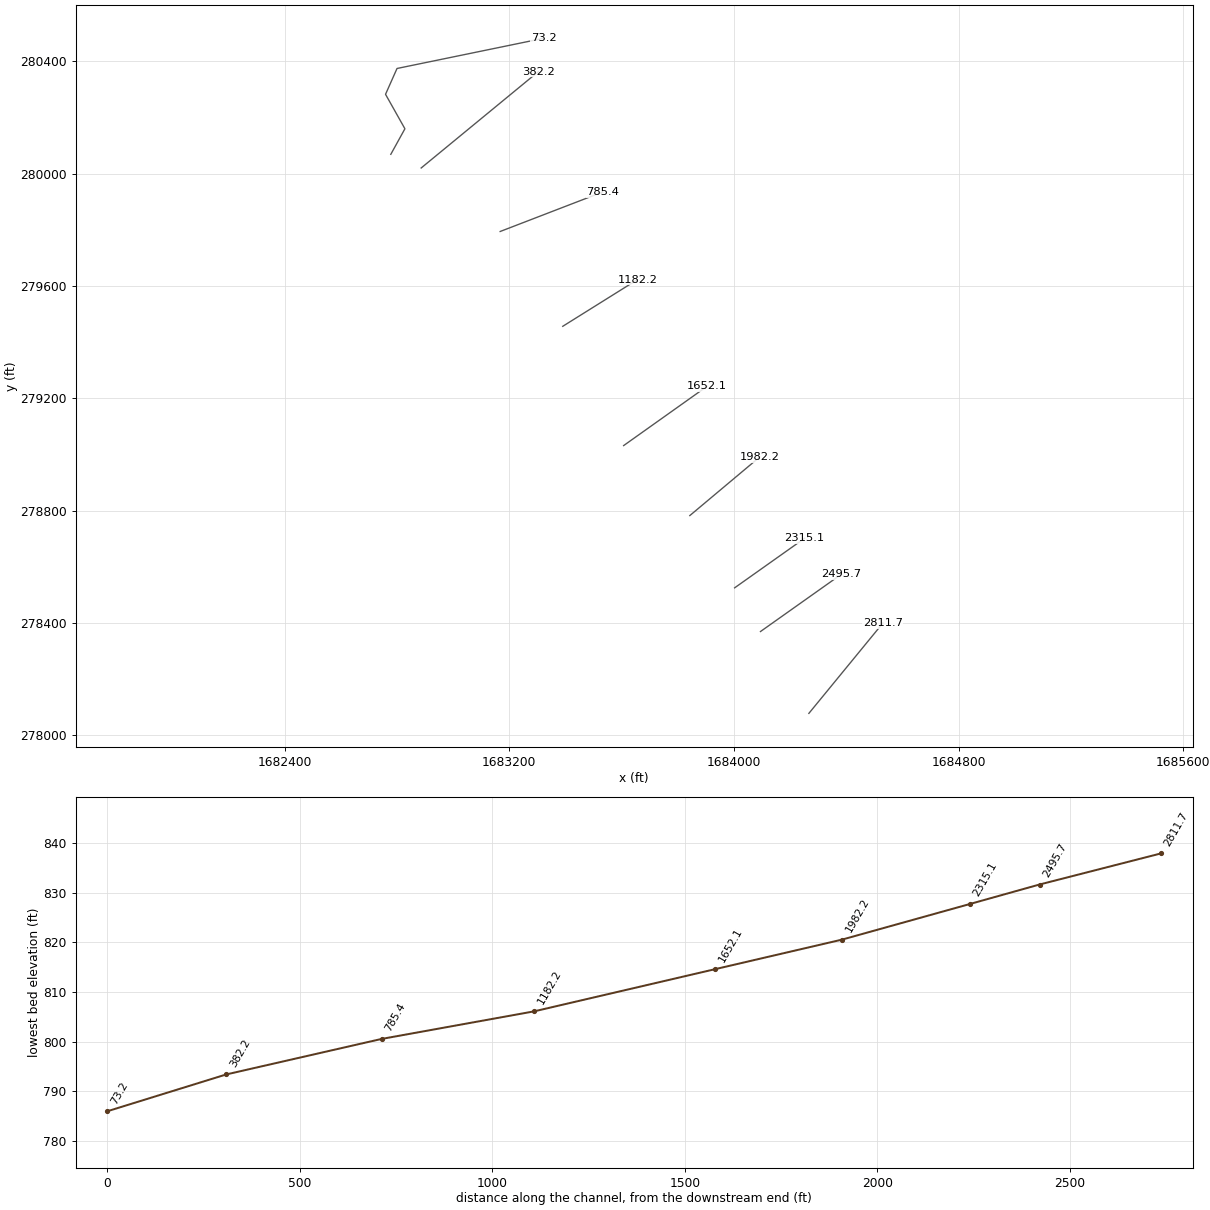
HEC-RAS study MIDDLEILCK.prj: MIDDLEILCK

--- MIDDLEILCK.g01 (geometry) --- (continued)

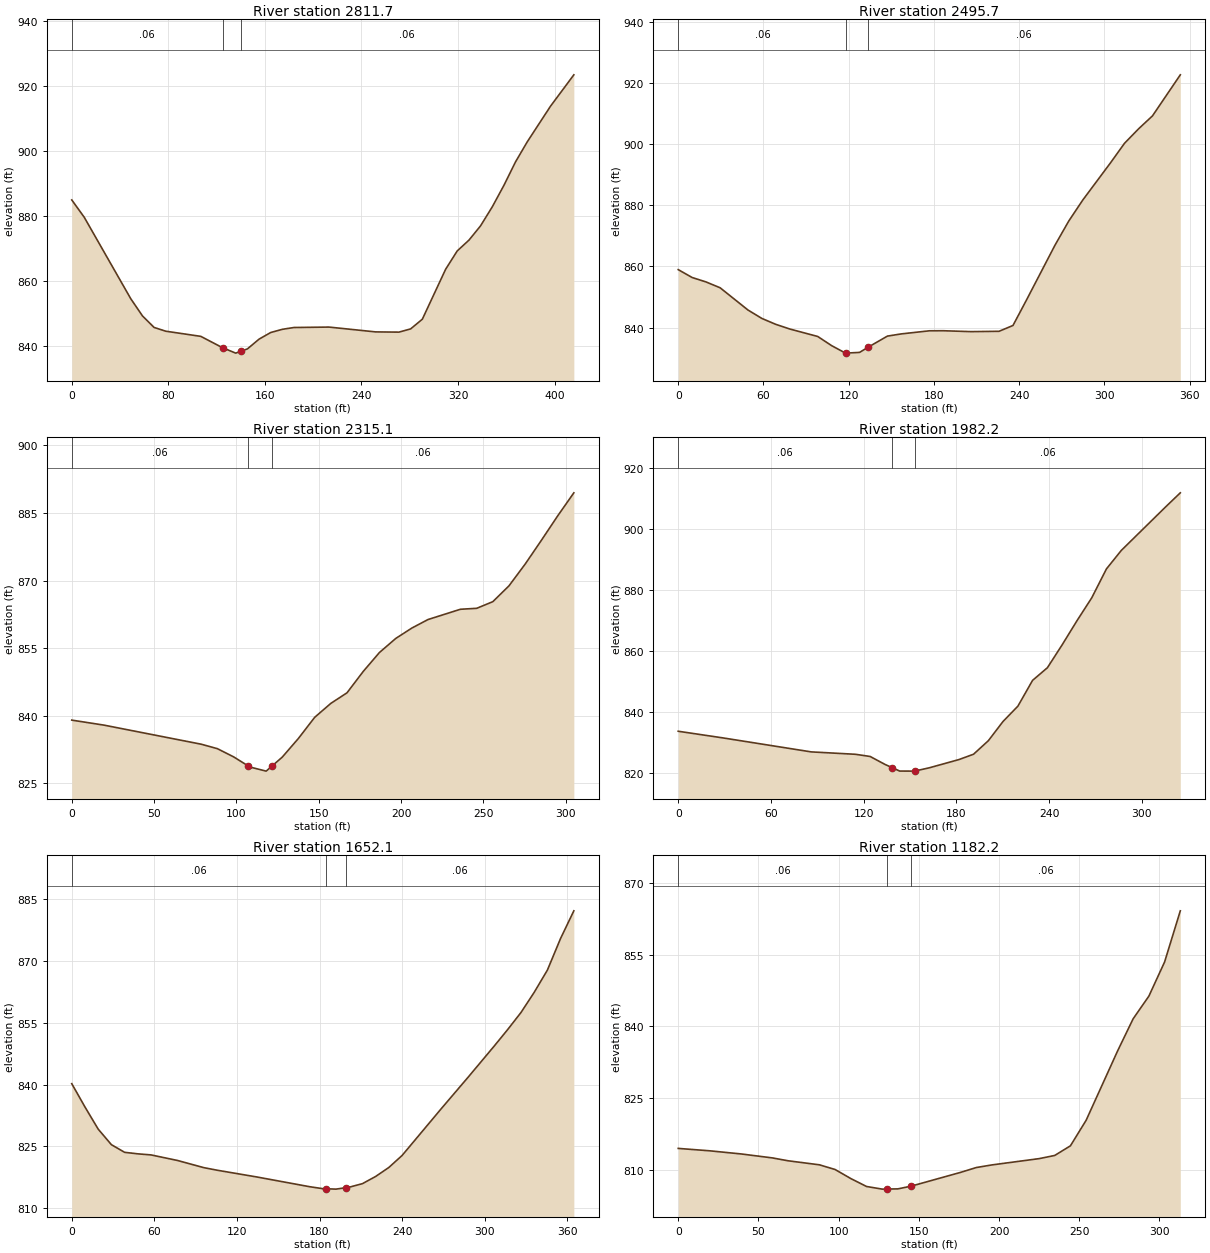
Type RM Length L Ch R = 1 ,2811.7  ,321.9,315.8,309.6
XS GIS Cut Line= 3
      1684266.58       278077.85     1684266.978      278078.336
     1684530.254      278399.505
#Sta/Elev= 30
       0  884.96    10.3  879.66    48.9   854.6    58.6  849.33    68.2   845.8
    77.9  844.64   106.9  843.06   124.9  839.57   135.8  837.91   139.9  838.46
   145.5  839.21   155.2  842.22   164.8  844.24   174.5  845.23   184.1  845.78
   213.1  845.91   251.7  844.43     271  844.36   280.7  845.35   290.4  848.33
   309.7  863.67   319.3   869.3     329  872.61   338.6  876.99   348.3  882.82
     358  889.46   367.6  896.66   377.3   902.8   396.6  913.77   415.9  923.39
#Mann= 3 , 0 , 0
       0     .06       0   124.9    .045       0   139.9     .06       0
Bank Sta=124.9,139.9
XS Rating Curve= 0 ,0
Exp/Cntr=0.3,0.1

Type RM Length L Ch R = 1 ,2495.7  ,180.6,180.6,180.5
XS GIS Cut Line= 2
     1684094.247      278369.249     1684382.739      278573.595
#Sta/Elev= 30
       0  858.95     9.8  856.37    19.6  854.92    29.5  853.01    49.1  845.74
    58.9  842.98    68.7  841.05    78.6  839.52    98.2  837.09     108  834.09
   117.8  831.64   118.4  831.65   127.7  831.88   133.4   833.5   147.3  837.21
   157.1  837.93   176.8  838.94   186.6  838.96   206.2  838.67   225.9  838.78
   235.7  840.69   245.5  849.28   265.2  866.89     275  874.87   284.8  881.69
   304.4  893.91   314.2  900.26   324.1  904.99   333.9  909.23   353.5  922.66
#Mann= 3 , 0 , 0
       0     .06       0   118.4    .045       0   133.4     .06       0
Bank Sta=118.4,133.4
XS Rating Curve= 0 ,0
Exp/Cntr=0.3,0.1

Type RM Length L Ch R = 1 ,2315.1  ,331.3,332.8,334.2
XS GIS Cut Line= 2
     1684002.226      278524.849     1684251.104      278701.136
#Sta/Elev= 27
       0  839.04    19.7  837.92    78.7  833.69    88.5   832.7    98.4  830.87
   106.9  828.93   108.2  828.63   118.1  827.72   121.9  828.93   127.9  830.84
   137.7  834.98   147.6  839.67   157.4  842.76   167.2   845.1   177.1  849.86
   186.9  854.04   196.8  857.16   206.6  859.47   216.4  861.36   236.1  863.64
     246  863.85   255.8  865.33   265.6  868.84   275.5   873.7   285.3  878.95
   295.2  884.37     305  889.48
#Mann= 3 , 0 , 0
       0     .06       0   106.9    .045       0   121.9     .06       0
Bank Sta=106.9,121.9
XS Rating Curve= 0 ,0
Exp/Cntr=0.3,0.1

Type RM Length L Ch R = 1 ,1982.2  ,331.4,330,328.6
XS GIS Cut Line= 2
     1683842.726      278782.198      1684091.73      278990.907
#Sta/Elev= 25
       0   833.6    28.7  831.44      86  826.84   114.7  826.05   124.2  825.33
   133.8  822.73   138.3   821.7   143.3  820.55   152.9  820.53   153.3  820.58
   162.4  821.61   181.6  824.31   191.1  826.07   200.7  830.51   210.2  836.82
   219.8  841.83   229.3  850.28   238.9  854.43   248.5  861.98     258  869.81
   267.6  877.35   277.1  886.82   286.7  892.87   315.4  907.15   324.9  911.76
#Mann= 3 , 0 , 0
       0     .06       0   138.3    .045       0   153.3     .06       0
Bank Sta=138.3,153.3
XS Rating Curve= 0 ,0
Exp/Cntr=0.3,0.1

Type RM Length L Ch R = 1 ,1652.1  ,470.9,469.6,468.3
XS GIS Cut Line= 2
     1683607.021      279031.373     1683904.365      279242.644
#Sta/Elev= 30
       0  840.21     9.6  834.54    19.2  829.16    28.8  825.38    38.4  823.52
      48  823.15    57.6  822.89    76.8  821.54      96  819.79   105.6  819.17
   134.4  817.53   172.8  815.16   182.4  814.68   184.5  814.66     192  814.57
   199.5  814.94   201.6  815.04   211.2   815.9   220.8  817.65   230.4  819.84
     240  822.75   268.8  834.26     288  841.79   307.2  849.46   316.8   853.4
   326.4  857.52     336  862.42   345.6  867.84   355.2  875.55   364.8  882.24
#Mann= 3 , 0 , 0
       0     .06       0   184.5    .045       0   199.5     .06       0
Bank Sta=184.5,199.5
XS Rating Curve= 0 ,0
Exp/Cntr=0.3,0.1

Type RM Length L Ch R = 1 ,1182.2  ,400.7,396.4,392.1
XS GIS Cut Line= 2
     1683390.239      279456.109     1683655.662      279621.969
#Sta/Elev= 25
       0  814.57    19.6  814.07    39.1  813.42    58.7  812.59    68.5  811.99
      88  811.15    97.8  810.17   107.6  808.28   117.4  806.63   127.2  806.08
   130.2   806.1   136.9  806.13   145.2   806.7     176  809.57   185.8  810.58
   195.6  811.13     225  812.44   234.7   813.1   244.5  815.11   254.3  820.44
   273.9  834.89   283.6   841.6   293.4  846.32   303.2  853.44     313  864.11
#Mann= 3 , 0 , 0
       0     .06       0   130.2    .045       0   145.2     .06       0
Bank Sta=130.2,145.2
XS Rating Curve= 0 ,0
Exp/Cntr=0.3,0.1

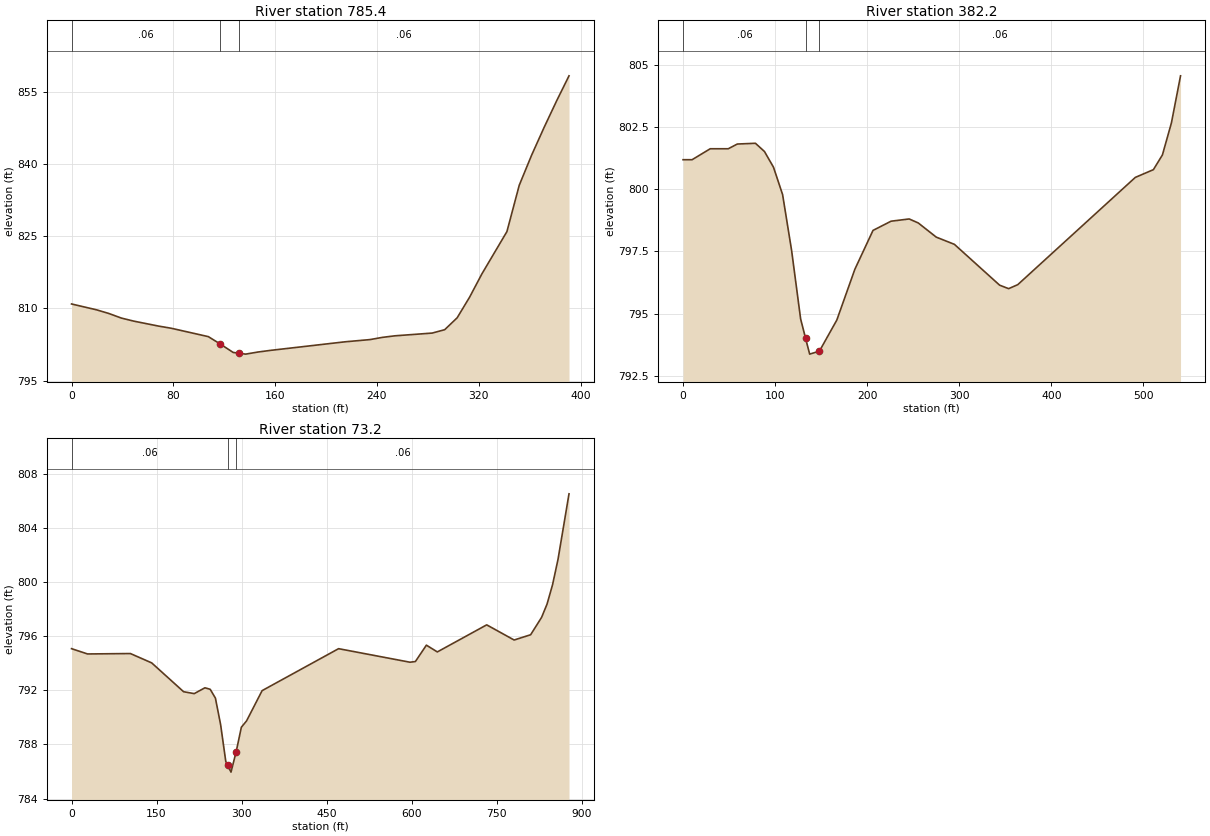
Type RM Length L Ch R = 1 ,785.4   ,396,403.3,410.7
XS GIS Cut Line= 2
      1683167.41      279793.695     1683532.215      279934.216
#Sta/Elev= 29
       0  810.93    19.6  809.72    29.3  808.96    39.1  808.01    48.9  807.37
    68.4  806.34    78.2   805.9   107.5  804.15   116.8  802.63     127  800.87
   131.8   800.7   136.8  800.52   146.6  800.96   156.4   801.3     215  803.08
   234.6  803.54   244.3     804   254.1  804.32   283.4  804.89   293.2  805.59
     303  808.06   312.8  812.35   322.5   817.2   342.1  825.95   351.8  835.58
   361.6  841.87   371.4  847.62   381.2  853.11   390.9  858.29
#Mann= 3 , 0 , 0
       0     .06       0   116.8    .045       0   131.8     .06       0
Bank Sta=116.8,131.8
XS Rating Curve= 0 ,0
Exp/Cntr=0.3,0.1

Type RM Length L Ch R = 1 ,382.2   ,298.6,309,319.4
XS GIS Cut Line= 2
     1682886.134       280019.82     1683303.444      280362.969
#Sta/Elev= 30
       0  801.18     9.8  801.18    29.5  801.62    49.1  801.62    58.9  801.81
    78.6  801.84    88.4  801.51    98.2  800.88   108.1  799.78   117.9  797.53
   127.7  794.78   133.1     794   137.5  793.37   148.1  793.49     167  794.74
   186.6  796.78   206.3  798.34   225.9  798.71   245.6   798.8   255.4  798.64
     275  798.07   294.7  797.78   343.8  796.14   353.6     796   363.5  796.16
   491.2  800.47   510.8  800.78   520.6  801.37   530.4  802.66   540.3  804.55
#Mann= 3 , 0 , 0
       0     .06       0   133.1    .045       0   148.1     .06       0
Bank Sta=133.1,148.1
XS Rating Curve= 0 ,0
Exp/Cntr=0.3,0.1

Type RM Length L Ch R = 1 ,73.2    ,66.7,73.2,79.7
XS GIS Cut Line= 5
     1682778.004      280068.483     1682828.215      280159.446
     1682759.213      280282.116     1682800.103      280374.119
     1683321.454      280481.456
#Sta/Elev= 30
       0  795.07    28.3  794.68   103.9  794.71   141.4  794.02   197.7  791.89
   216.5  791.75   235.3  792.18   244.6  792.07   253.8  791.42     263  789.46
   272.1  786.74   275.5  786.45   281.3  785.95   290.5  787.47   299.6  789.27
   308.7  789.73   336.2  791.97   471.1  795.07     597  794.07   606.6  794.12
     626  795.33   645.3  794.83   732.4  796.83   780.8  795.71   809.9   796.1
   829.2  797.38   838.9  798.37   848.6   799.8   858.3  801.69   877.6  806.51
#Mann= 3 , 0 , 0
       0     .06       0   275.5    .045       0   290.5     .06       0
Bank Sta=275.5,290.5
XS Rating Curve= 0 ,0
Exp/Cntr=0.3,0.1

Chan Stop Cuts=-1
Use User Specified Reach Order=0
Composite Channel Slope=5